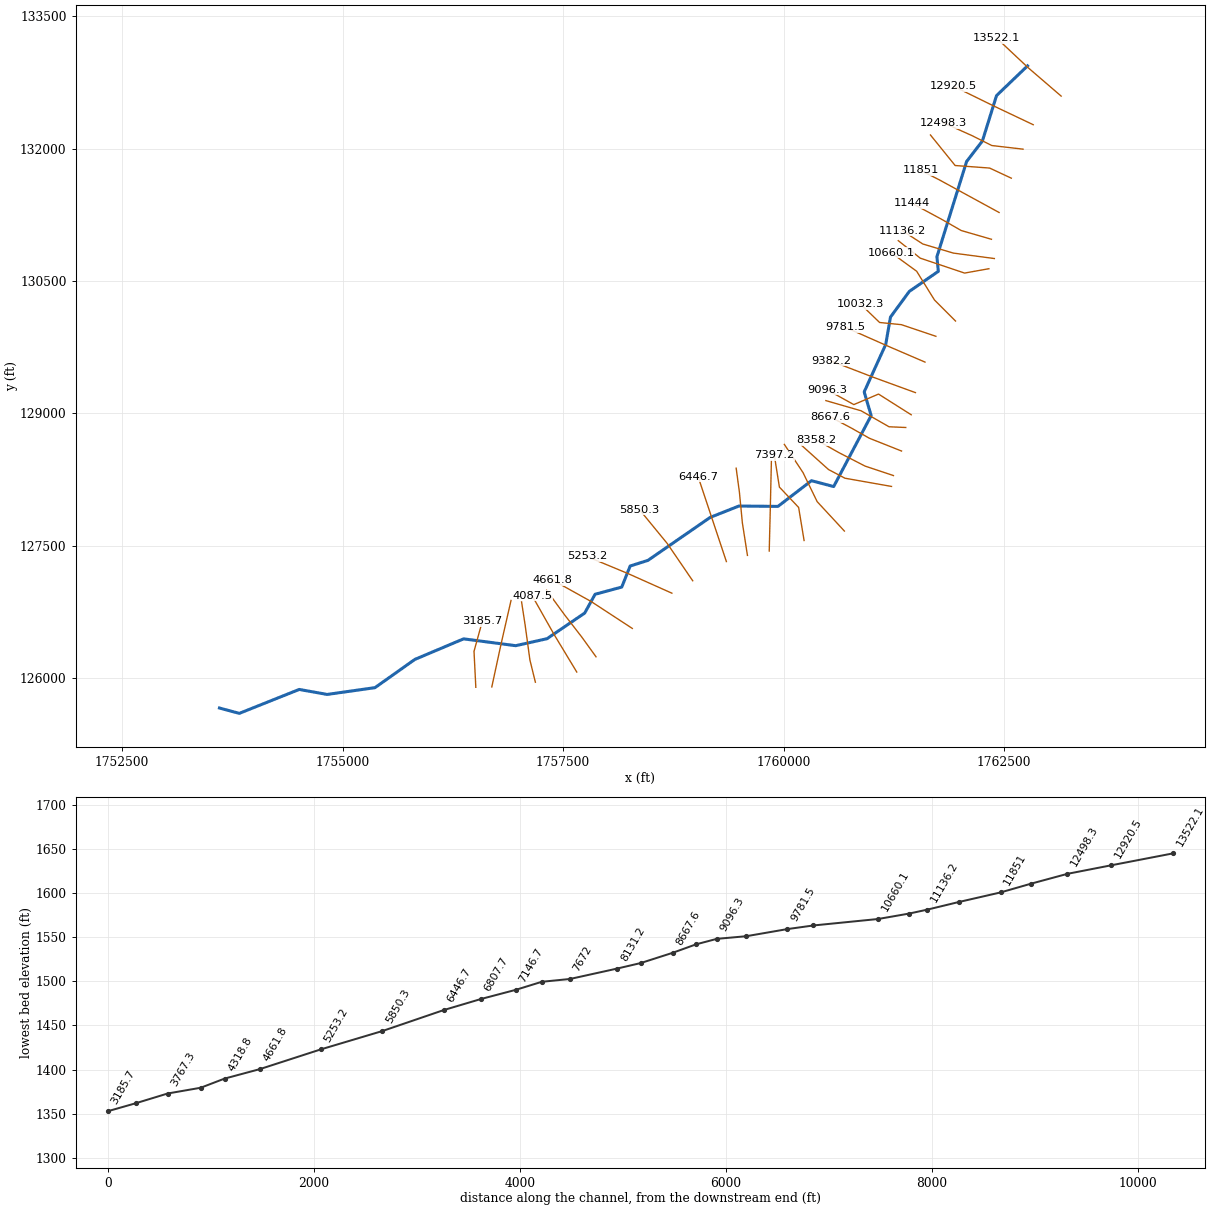
--- Bartley Creek.prj (project) ---

Proj Title=Bartley Creek
Current Plan=p01
Default Exp/Contr=0,0
English Units
Geom File=g01
Flow File=f01
Plan File=p01
BEGIN DESCRIPTION:
END DESCRIPTION:
DSS Export Rating Curves= 0
DSS Export Rating Curve Sorted= 0
DSS Export Volume Flow Curves= 0
DXF OffsetX= 0
DXF OffsetY= 0
DXF ScaleX= 0
DXF ScaleY= 0

--- Bartley Creek.p01 (plan) ---

Plan Title=Floodplain
Program Version=4.00
Geom File=g01
Flow File=f01
K Sum by GR=0
Std Step Tol=0.01
Critical Tol=0.01
Num of Std Step Trials=20
Max Error Tol=0.3
Flow Tol Ratio=0.001
Split Flow NTrial=30
Split Flow Tol=0.02
Split Flow Ratio=0.02
Log Output Level=0
Friction Slope Method=1
Unsteady Friction Slope Method=2
Unsteady Bridges Friction Slope Method=1
Global Log Level=0
CheckData=False
Run HTab=0
Run UNet=0
Run PostProcess=0
UNET Theta=0
UNET Theta Warmup=0
UNET ZTol=0
UNET ZSATol=0
UNET MxIter=0
UNET MaxInSteps=0
UNET DtIC=0
UNET DtMin=0
UNET MaxCRTS=0
UNET WFStab=0
UNET SFStab=0
UNET WFX=0
UNET SFX=0
UNET DSS MLevel=0
UNET DZMax Abort=0
UNET Convert EG Bridges=0
UNET Use Existing IB Tables=0
UNET Froude Limit=0
UNET Froude Power=0
Write IC File=0
Echo Input=False
Echo Output=False
Write Detailed=0

--- Bartley Creek.f01 (steady flow) ---

Flow Title=NFF Regression Equation
Program Version=4.00
Number of Profiles=1
Profile Names=P100yr
River Rch & RM=Bartley Creek,Main      ,13522.1
595.4103
River Rch & RM=Bartley Creek,Main      ,13522.1
695.6560
River Rch & RM=Bartley Creek,Main      ,12146.6
626.9614
River Rch & RM=Bartley Creek,Main      ,10660.1
874.6181
River Rch & RM=Bartley Creek,Main      ,10032.3
909.5049
River Rch & RM=Bartley Creek,Main      ,7397.2
1000.170
River Rch & RM=Bartley Creek,Main      ,2687.5
1102.855
River Rch & RM=Bartley Creek,Main      ,2374.8
1559.024
River Rch & RM=Bartley Creek,Main      ,293.3
1591.494
Boundary for River Rch & Prof#=Bartley Creek,Main      ,1
Up Type=0
Dn Type=3
Dn Slope=0.02271

--- Bartley Creek.g01 (geometry) ---

Geom Title=USGS 10m DEM
Program Version=4.00

River Reach=Bartley Creek   ,Main
Reach XY= 30
     1762766.306      132936.389     1762414.906      132600.021
     1762254.749      132085.782     1762075.162      131852.268
     1761738.929      130773.323     1761754.538      130608.314
     1761425.986       130380.98     1761212.138      130089.703
     1761158.461      129780.209      1760914.06      129242.211
     1760993.201      128974.056     1760568.278      128169.658
     1760316.312      128236.054     1759936.334       127944.86
     1759493.401      127948.752     1759167.737      127820.019
     1758462.119      127333.176     1758260.477      127269.073
     1758165.459      127030.764     1757862.784      126948.773
     1757744.779      126735.751     1757317.202      126445.336
      1756962.42       126366.41     1756371.628      126443.803
     1755819.149      126210.858      1755367.04        125890.8
     1754824.534      125813.932     1754508.066      125870.635
     1753828.387      125599.377     1753603.515      125660.033

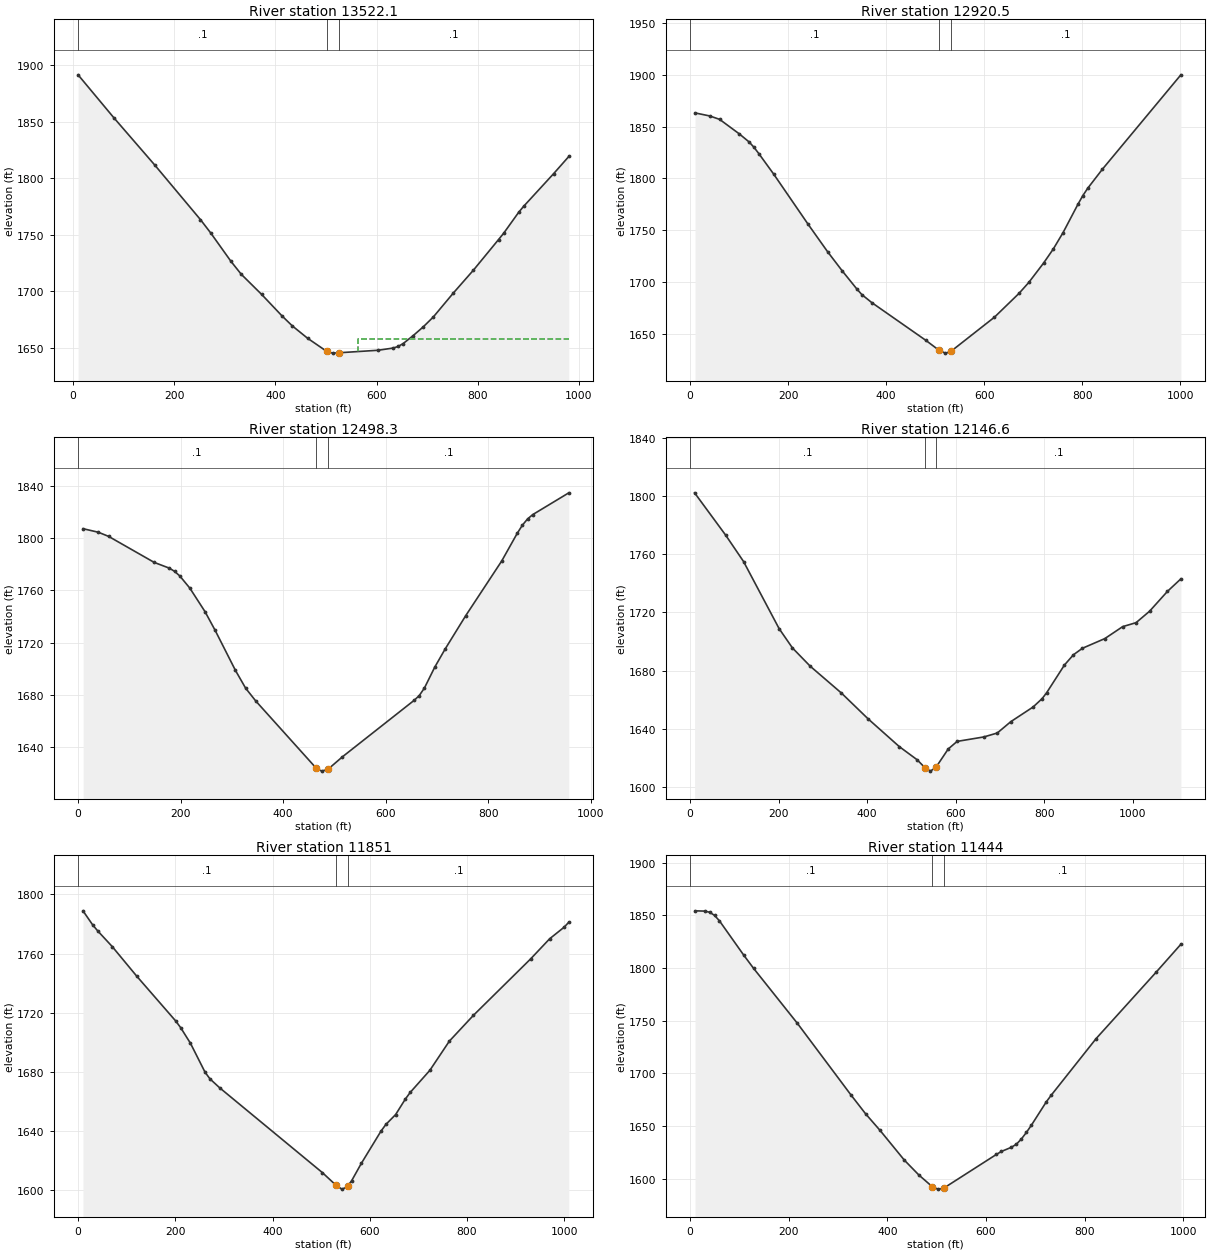
Type RM Length L Ch R = 1 ,13522.1 ,593.5,601.6,609.8
XS GIS Cut Line= 3
     1763147.844      132593.985     1762773.355      132915.952
     1762419.045      133248.669
#Sta/Elev= 30
    10.1 1891.49    80.6 1853.58   161.3 1811.81     252 1763.28   272.1 1751.59
   312.4 1726.27   332.6 1714.92   372.9 1697.09   413.2 1678.04   433.4 1669.27
   463.6 1658.32   501.2 1646.78   503.8 1646.08   513.7 1645.13   526.2 1645.46
     603 1647.67   632.7 1649.62   642.7 1651.03   652.6 1653.62   672.4 1660.66
   692.3  1668.4   712.1 1677.11   751.8 1698.38   791.4 1718.58     841 1745.64
     851 1751.15   880.7 1769.71   890.6 1775.07   950.2 1804.14   979.9  1819.2
#Mann= 3 , 0 , 0
    10.1      .1       0   501.2    .045       0   526.2      .1       0
#XS Ineff= 2 , 0
                          563.69         1657.94
Permanent Ineff=
       F       F
Bank Sta=501.2,526.2
XS Rating Curve= 0 ,0
Exp/Cntr=0.3,0.1

Type RM Length L Ch R = 1 ,12920.5 ,422.6,422.2,421.9
XS GIS Cut Line= 3
     1762831.223      132269.709     1762378.959      132484.203
     1761929.535      132704.451
#Sta/Elev= 30
      10 1863.22      40 1860.29    60.1    1857   100.1 1843.06   120.1 1835.28
   130.1 1830.13   140.2  1823.9   170.2 1804.35   240.3 1756.06   280.3 1729.41
   310.3 1710.85   340.4 1693.22   350.4 1687.95   370.4 1680.34   480.5 1643.99
   508.1 1634.18   520.6 1631.58   530.6  1632.8   533.1 1633.72   620.7 1666.22
   670.7 1689.13   690.7 1699.69   720.8 1718.34   740.8 1732.04   760.8  1747.9
   790.8 1774.93   800.8 1783.31   810.9 1790.52   840.9 1808.92    1001 1899.95
#Mann= 3 , 0 , 0
       0      .1       0   508.1    .045       0   533.1      .1       0
Bank Sta=508.1,533.1
XS Rating Curve= 0 ,0
Exp/Cntr=0.3,0.1

Type RM Length L Ch R = 1 ,12498.3 ,340.7,351.7,362.8
XS GIS Cut Line= 4
     1762715.505      131992.829       1762361.4      132034.004
     1762139.055      132145.177     1761817.889       132289.29
#Sta/Elev= 30
     9.9 1807.02    39.6 1804.33    59.4  1801.2   148.5  1781.3   178.2 1776.89
   188.1 1774.49   198.1 1771.08   217.9 1761.71   247.6  1743.7   267.4 1729.38
     307  1698.8   326.8 1685.27   346.6 1675.48   463.3  1624.7   465.9 1623.64
   475.8 1621.95   488.3 1623.66   515.6 1632.88   655.4 1675.98   665.4 1679.62
   675.5  1685.4   695.6  1701.3   715.7 1715.05   755.9 1740.55   826.3 1782.42
   856.5 1803.51   866.6 1809.74   876.6 1814.47   886.7 1817.79   957.1 1834.43
#Mann= 3 , 0 , 0
       0      .1       0   463.3    .045       0   488.3      .1       0
Bank Sta=463.3,488.3
XS Rating Curve= 0 ,0
Exp/Cntr=0.3,0.1

Type RM Length L Ch R = 1 ,12146.6 ,307.5,295.6,283.6
XS GIS Cut Line= 4
     1762582.545      131664.077     1762336.695      131778.719
     1761945.532      131807.541     1761665.541      132153.412
#Sta/Elev= 30
      10 1802.12    80.4 1772.96   120.6 1754.92   200.9 1708.82   231.1  1695.5
   271.3 1682.93   341.7 1664.51     402 1646.76   472.4  1627.7   512.6 1618.68
   530.3 1613.24   542.8 1610.84   555.3 1613.49     583 1626.08   603.1 1631.28
   663.5 1634.34   693.8 1637.04   724.2 1644.81   774.7 1654.92     795 1660.66
   805.1 1664.63   845.5 1683.78   865.8 1690.81     886 1695.27   936.6 1701.92
     977 1710.15  1007.3 1712.88  1037.7 1720.72  1078.1 1734.37  1108.5 1742.99
#Mann= 3 , 0 , 0
       0      .1       0   530.3    .045       0   555.3      .1       0
Bank Sta=530.3,555.3
XS Rating Curve= 0 ,0
Exp/Cntr=0.3,0.1

Type RM Length L Ch R = 1 ,11851   ,407.4,406.9,406.4
XS GIS Cut Line= 3
      1762443.75      131275.334     1761764.361      131645.909
     1761554.369      131752.965
#Sta/Elev= 30
    10.1 1788.82    30.2 1779.25    40.2 1775.34    70.4 1764.63   120.6 1744.73
     201 1714.39   211.1 1709.92   231.2  1699.4   261.3 1679.81   271.4 1675.33
   291.5 1669.27   502.5 1612.09   530.2 1603.67   542.7 1600.91   552.8 1602.23
   555.2 1603.27   562.8 1606.57   582.9 1618.38   623.1 1640.02   633.2 1644.57
   653.3 1651.25   673.4 1661.77   683.4 1666.24   723.6 1681.07   763.8 1700.82
   813.2  1718.2     931 1756.34   970.3 1769.98   999.8 1777.72  1009.6 1781.12
#Mann= 3 , 0 , 0
       0      .1       0   530.2    .045       0   555.2      .1       0
Bank Sta=530.2,555.2
XS Rating Curve= 0 ,0
Exp/Cntr=0.3,0.1

Type RM Length L Ch R = 1 ,11444   ,301.5,307.9,314.2
XS GIS Cut Line= 4
     1762357.282      130971.688     1762015.529      131070.508
     1761784.949      131202.268     1761455.548      131379.321
#Sta/Elev= 30
     9.9 1854.14    29.6 1853.88    39.5  1852.8    49.4 1849.85    59.3 1844.73
   108.7 1812.08   128.5 1799.64   217.4 1747.42   326.1 1679.43   355.8 1661.53
   385.3 1645.66   434.4 1617.54   463.9  1603.4   490.8 1592.44   493.5 1591.46
   503.3    1590   513.1 1590.68   515.8 1591.37   621.3 1622.98   631.4 1625.78
   651.6 1629.72   661.8 1632.68   671.9 1637.65     682 1643.82   692.1 1650.66
   722.4 1672.86   732.5 1679.25   823.5 1732.94   944.8 1795.72   995.3  1822.4
#Mann= 3 , 0 , 0
       0      .1       0   490.8    .045       0   515.8      .1       0
Bank Sta=490.8,515.8
XS Rating Curve= 0 ,0
Exp/Cntr=0.3,0.1

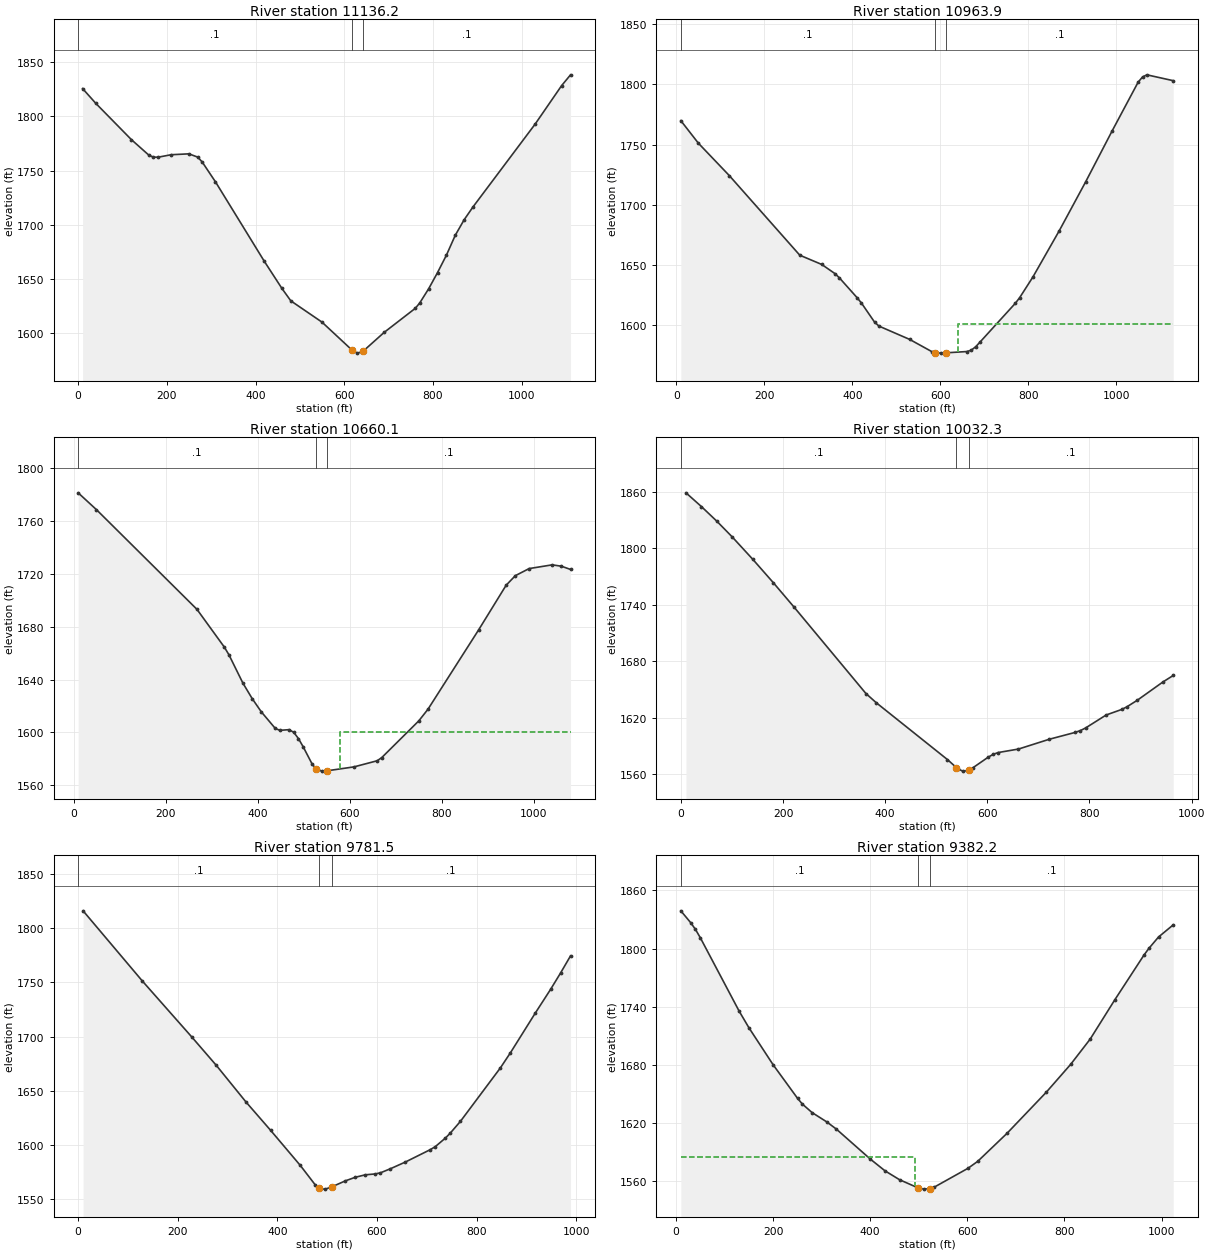
Type RM Length L Ch R = 1 ,11136.2 ,173.6,172.3,170.9
XS GIS Cut Line= 4
     1762390.222       130753.46     1761924.944      130815.222
     1761579.074       130918.16     1761344.376      131070.508
#Sta/Elev= 30
      10  1825.7    39.9 1811.99   119.8 1778.62   159.8 1764.04   169.8 1762.36
   179.8 1762.28   209.7 1764.58   249.7 1765.41   269.6 1762.36   279.6  1757.9
   309.6 1739.51   419.4 1666.29   459.4 1641.03   479.4  1629.6   549.6 1609.97
   617.2 1584.18   629.7  1581.3   642.2    1583   689.9 1600.48   760.1 1622.72
   770.1 1627.68   790.1 1640.73   810.2 1655.74   830.2 1671.81   850.2 1690.23
   870.2 1704.55   890.2 1716.42  1030.1 1792.83    1090 1828.49    1110  1838.4
#Mann= 3 , 0 , 0
       0      .1       0   617.2    .045       0   642.2      .1       0
Bank Sta=617.2,642.2
XS Rating Curve= 0 ,0
Exp/Cntr=0.3,0.1

Type RM Length L Ch R = 1 ,10963.9 ,324.1,303.8,283.3
XS GIS Cut Line= 4
      1762328.46       130638.17     1762052.587      130588.759
     1761550.251      130757.577     1761300.741      130956.008
#Sta/Elev= 30
      10 1769.94      50 1751.17   120.1 1724.35   280.3 1658.24   330.3 1650.54
   360.3 1642.94   370.3 1639.45   410.2 1623.11   420.2 1618.66   450.2 1602.72
   460.2 1599.38   530.2 1588.29   580.2 1578.22   587.7 1577.42   600.2 1576.93
   612.7 1577.17   660.2 1578.25   670.2 1579.42   680.2 1582.26   690.2 1586.22
   770.2 1618.32   780.2 1623.08   810.2 1640.19     870 1678.54   929.8    1719
   989.5 1760.95  1049.3 1801.91  1059.3 1806.22  1069.2 1807.99    1129 1803.13
#Mann= 3 , 0 , 0
      10      .1       0   587.7    .045       0   612.7      .1       0
#XS Ineff= 2 , 0
                          640.95         1601.31
Permanent Ineff=
       F       F
Bank Sta=587.7,612.7
XS Rating Curve= 0 ,0
Exp/Cntr=0.3,0.1

Type RM Length L Ch R = 1 ,10660.1 ,602.3,627.8,653.3
XS GIS Cut Line= 4
     1761949.649      130045.249     1761710.834      130284.064
     1761509.076      130609.347     1761217.926      130820.861
#Sta/Elev= 30
     9.9 1781.22    49.7 1768.48   268.2 1693.09   327.8 1664.48   337.7 1658.73
     368 1637.34   388.1 1625.66   408.2 1615.52   438.5 1603.02   448.5 1601.58
   468.7  1602.1   478.8 1600.01   488.8 1595.35   498.9 1589.28     519 1575.81
   526.7 1572.71   539.2 1570.73   551.7 1571.01   609.7 1573.95   660.1 1578.58
   670.1 1581.02   750.5 1608.75   770.5 1617.57   880.5 1677.52   940.4 1711.34
   960.4 1718.57   990.4 1723.93  1040.4 1726.74  1060.4 1725.73  1080.4 1723.27
#Mann= 3 , 0 , 0
     9.9      .1       0   526.7    .045       0   551.7      .1       0
#XS Ineff= 2 , 0
                          578.77         1600.61
Permanent Ineff=
       F       F
Bank Sta=526.7,551.7
XS Rating Curve= 0 ,0
Exp/Cntr=0.3,0.1

Type RM Length L Ch R = 1 ,10032.3 ,259.5,250.8,242
XS GIS Cut Line= 4
     1761727.304      129872.313     1761336.141      130004.074
      1761089.09      130028.779     1760870.863      130238.771
#Sta/Elev= 30
    10.1    1859    40.3 1844.39    70.5 1828.85   100.7 1812.09   140.9 1788.35
   181.2 1763.46   221.5 1737.71   362.4  1645.8   382.6 1636.04     522 1575.65
   539.3 1567.25   541.9 1565.99   551.8  1563.4   561.7  1563.9   564.3 1564.69
   571.7 1566.94   601.5 1578.14   611.4  1581.2   621.3 1583.15     661 1586.85
   721.6 1597.31   772.1 1604.55   782.2 1606.49   792.3 1609.22   832.7 1623.05
   862.9 1628.87     873 1631.64   893.2 1638.54   943.7 1658.08   963.9    1665
#Mann= 3 , 0 , 0
       0      .1       0   539.3    .045       0   564.3      .1       0
Bank Sta=539.3,564.3
XS Rating Curve= 0 ,0
Exp/Cntr=0.3,0.1

Type RM Length L Ch R = 1 ,9781.5  ,397.7,399.3,400.7
XS GIS Cut Line= 3
     1761603.779       129579.97     1761194.022      129756.056
     1760697.927      129975.251
#Sta/Elev= 30
     9.9 1815.94   128.8 1751.25     228 1699.66   277.5 1673.35     337 1639.62
   386.5 1613.46     446 1581.12   476.1 1563.13   483.7 1560.44   486.2 1559.55
   496.2 1559.32   508.7 1561.33   536.4 1566.95   556.5 1570.28   576.6 1572.53
   596.6 1573.33   606.7 1574.35   626.8 1578.11   656.9 1584.32   707.1 1595.79
   717.2 1598.61   737.3 1606.44   747.3 1611.14   767.4 1621.84   847.7 1671.19
   867.8  1685.1     918 1721.93   948.2 1743.42   968.3 1758.55   988.4 1774.43
#Mann= 3 , 0 , 0
       0      .1       0   483.7    .045       0   508.7      .1       0
Bank Sta=483.7,508.7
XS Rating Curve= 0 ,0
Exp/Cntr=0.3,0.1

Type RM Length L Ch R = 1 ,9382.2  ,264.4,285.9,307.6
XS GIS Cut Line= 3
     1761495.228      129234.023       1761024.9       129405.45
     1760536.242      129593.324
#Sta/Elev= 30
      10 1838.98      30 1826.91      40 1819.88    50.1 1811.18   130.2 1735.15
   150.2  1718.1   200.2 1679.72   250.3 1645.16   260.3 1639.16   280.3 1630.38
   310.4 1620.79   330.4 1613.26   400.5 1582.18   430.5 1570.14   460.5 1560.95
   498.2  1552.6   510.7 1551.22   523.2 1551.73   530.8 1552.95   601.3 1572.72
   621.4 1579.92   681.8 1608.91   762.4 1651.27   812.7 1680.12     853 1706.29
   903.3 1746.58   963.7 1793.11   973.8 1800.03   993.9 1811.94  1024.1 1824.46
#Mann= 3 , 0 , 0
      10      .1       0   498.2    .045       0   523.2      .1       0
#XS Ineff= 2 , 0
          491.61 1584.69
Permanent Ineff=
       F       F
Bank Sta=498.2,523.2
XS Rating Curve= 0 ,0
Exp/Cntr=0.3,0.1

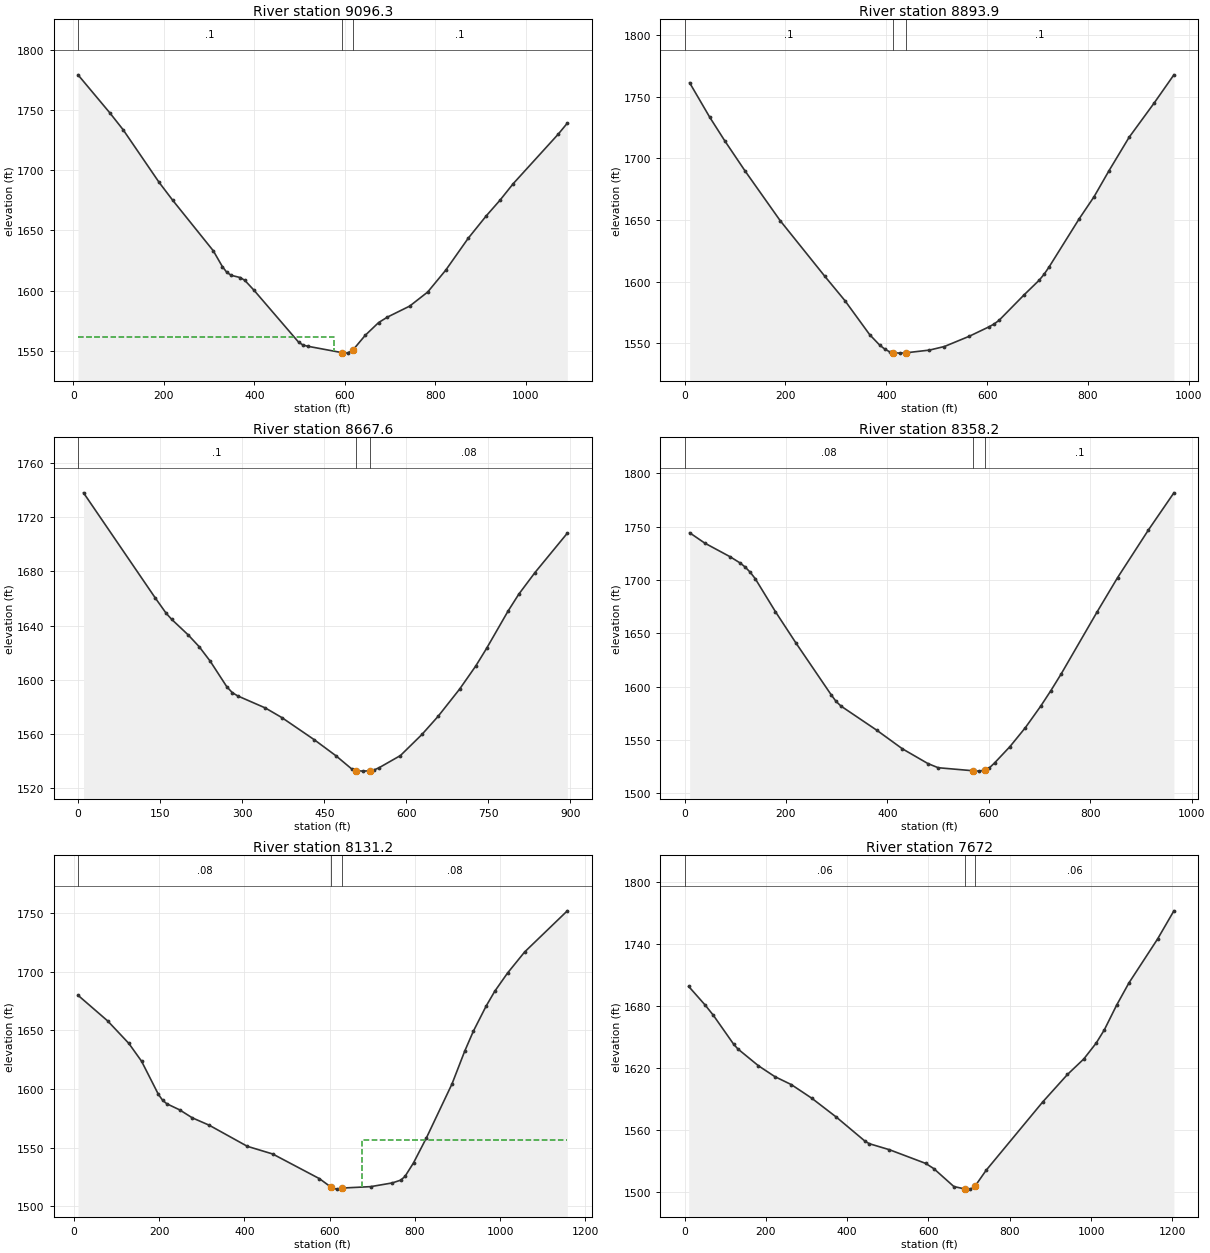
Type RM Length L Ch R = 1 ,9096.3  ,228.8,202.4,174.8
XS GIS Cut Line= 4
     1761447.313      128982.932     1761076.738       129217.63
     1760796.748      129098.222     1760492.052       129267.04
#Sta/Elev= 30
      10 1779.04    79.8 1747.74   109.7 1733.52   189.4 1689.76   219.3 1675.01
     309 1633.09     329 1620.03     339 1615.16   348.9 1612.74   368.9 1610.87
   378.8 1608.53   398.8 1600.45   497.6 1557.28   507.4 1554.93   517.2 1553.97
   593.1 1548.65   605.6 1548.23   618.1 1551.04   644.8 1563.01   674.3 1573.56
   693.9 1578.13     743 1587.23   782.8  1598.9   822.7 1617.05   872.4 1643.52
   912.2 1662.06   942.1 1674.83   971.9 1688.81  1071.5 1729.91  1091.4 1738.97
#Mann= 3 , 0 , 0
      10      .1       0   593.1    .045       0   618.1      .1       0
#XS Ineff= 2 , 0
          576.66  1561.3
Permanent Ineff=
       F       F
Bank Sta=593.1,618.1
XS Rating Curve= 0 ,0
Exp/Cntr=0.3,0.1

Type RM Length L Ch R = 1 ,8893.9  ,226.2,226.3,227.6
XS GIS Cut Line= 4
     1761385.551      128838.819     1761196.146      128847.054
     1760879.098      129028.225       1760479.7      129143.515
#Sta/Elev= 30
      10  1761.3    49.9 1733.32    79.8 1714.14   119.7  1689.9   189.6 1649.43
   278.4 1604.16   317.9  1584.6   367.2 1556.89     387 1548.45   396.8 1545.32
   406.7 1543.01   413.9 1542.36   426.4 1541.97   438.9 1542.22   485.7 1544.44
   515.3 1547.34   564.6 1555.66   604.2  1563.4   614.1 1565.67     624 1568.72
   673.5 1589.32   703.2 1601.11   713.1 1606.02     723 1611.95   782.4 1650.84
   812.1 1668.88   841.8 1690.04   881.4 1716.95   930.9 1744.66   970.4 1767.73
#Mann= 3 , 0 , 0
       0      .1       0   413.9    .045       0   438.9      .1       0
Bank Sta=413.9,438.9
XS Rating Curve= 0 ,0
Exp/Cntr=0.3,0.1

Type RM Length L Ch R = 1 ,8667.6  ,308.4,309.5,310.5
XS GIS Cut Line= 4
     1761337.774       128572.17     1760972.857      128717.101
     1760776.164      128828.388     1760532.886      128957.791
#Sta/Elev= 30
    10.1 1738.12   140.9 1660.58   161.1  1649.1   171.2 1644.59   201.4 1633.08
   221.5 1624.36   241.6 1613.67   271.8 1594.85   281.9 1590.44     292 1587.97
   342.3  1579.1   372.5 1571.99   431.9 1555.57   471.3 1543.78   500.7 1533.83
   507.9  1532.8   520.4  1532.4   532.9 1532.67     540 1533.11   549.9 1534.85
   589.2 1543.91   628.5 1559.49     658 1572.88   697.4 1593.06   726.9 1610.14
   746.6  1623.1   785.9 1650.72   805.6 1663.26   835.1  1679.2   894.2  1708.3
#Mann= 3 , 0 , 0
       0      .1       0   507.9    .045       0   532.9     .08       0
Bank Sta=507.9,532.9
XS Rating Curve= 0 ,0
Exp/Cntr=0.3,0.1

Type RM Length L Ch R = 1 ,8358.2  ,227.3,227,226.6
XS GIS Cut Line= 4
     1761246.026      128294.136     1760924.861      128401.191
     1760628.401      128553.539     1760373.115      128697.651
#Sta/Elev= 30
      10 1744.13    39.8 1734.44    89.6 1721.71   109.5 1715.85   119.5 1712.01
   129.4 1707.15   139.4 1701.07   179.2 1670.19   219.1 1641.23   288.8 1592.53
   298.7 1586.14   308.7 1581.67   378.9 1559.17   429.4 1541.76   479.9 1527.88
   500.1 1523.99   568.4 1521.16   580.9  1520.8   593.4 1521.95   601.1 1523.87
   611.3 1528.46   641.6 1543.75   671.9 1561.43   702.2 1581.59   722.4 1596.26
   742.6 1611.81   813.4 1669.87   853.8 1702.01   914.5 1746.58     965 1781.55
#Mann= 3 , 0 , 0
       0     .08       0   568.4    .045       0   593.4      .1       0
Bank Sta=568.4,593.4
XS Rating Curve= 0 ,0
Exp/Cntr=0.3,0.1

Type RM Length L Ch R = 1 ,8131.2  ,478.6,459.3,439.9
XS GIS Cut Line= 4
     1761223.899       128171.02     1760695.934       128264.19
     1760509.594      128362.537     1760203.827      128637.061
#Sta/Elev= 30
     9.9 1679.78    79.4 1657.95   129.1 1638.77   158.9 1623.63   198.6 1595.24
   208.5 1590.26   218.4 1587.28   248.2 1582.17     278 1575.34   317.7 1569.05
   407.1 1551.07   466.6 1544.53   576.3  1523.5   603.9 1516.15   616.4 1514.59
   628.9 1515.49   696.7 1516.72   746.8 1519.86   766.9 1522.24   776.9 1525.42
   796.9 1536.96     827 1558.15   887.1 1604.18   917.2 1632.34   937.3 1649.19
   967.3 1670.62   987.4 1683.17  1017.4 1698.69  1057.5 1716.66  1157.7 1751.74
#Mann= 3 , 0 , 0
     9.9     .08       0   603.9    .045       0   628.9     .08       0
#XS Ineff= 2 , 0
                          675.45          1556.7
Permanent Ineff=
       F       F
Bank Sta=603.9,628.9
XS Rating Curve= 0 ,0
Exp/Cntr=0.3,0.1

Type RM Length L Ch R = 1 ,7672    ,266.2,274.7,283.2
XS GIS Cut Line= 4
     1760689.692       127665.33     1760380.879      127998.848
     1760220.297      128328.248     1760008.835       128647.41
#Sta/Elev= 30
    10.1 1699.21    50.5 1681.21    70.7 1671.27   121.2 1642.94   131.3 1638.56
   181.8 1622.27   222.2 1611.76   262.6 1604.05   313.1  1590.8   373.7 1572.43
   444.4 1549.06   454.5 1546.77   504.1 1540.92   593.2 1527.66     613 1522.65
   662.5 1505.24   689.6  1502.9   702.1 1502.74     712 1504.37   714.6 1505.65
   741.8 1520.96   881.4 1587.39   941.9 1613.85   982.2 1628.93  1012.4 1644.18
  1032.6 1657.09  1062.8 1680.97    1093 1702.51  1163.5 1745.09  1203.8 1772.48
#Mann= 3 , 0 , 0
       0     .06       0   689.6    .045       0   714.6     .06       0
Bank Sta=689.6,714.6
XS Rating Curve= 0 ,0
Exp/Cntr=0.3,0.1

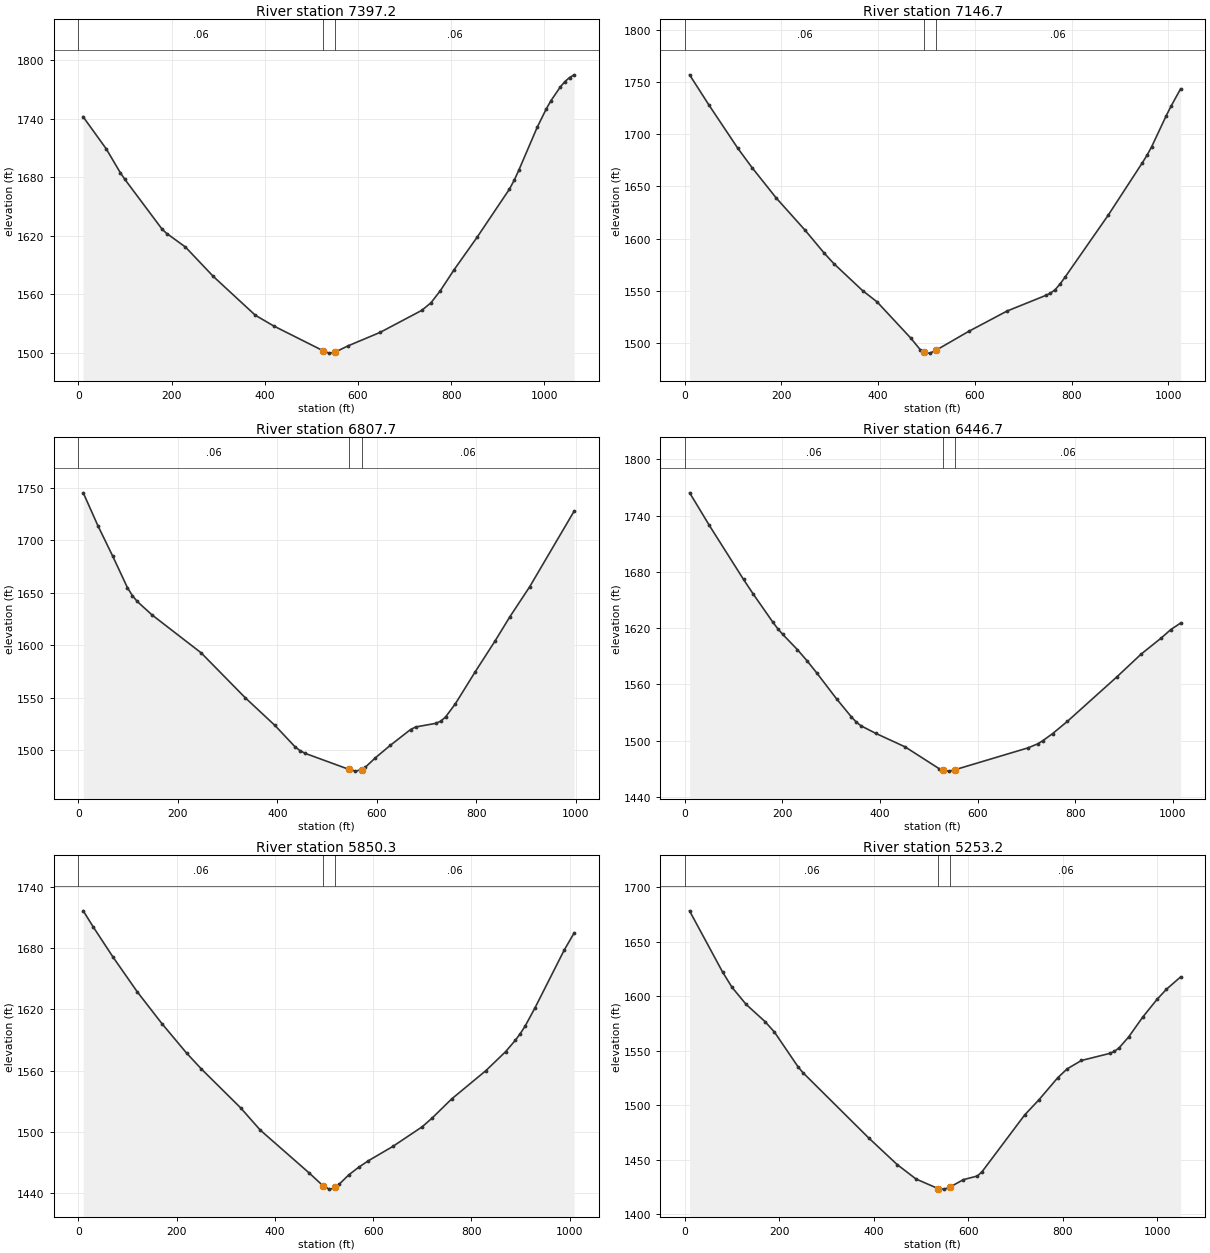
Type RM Length L Ch R = 1 ,7397.2  ,272.3,250.6,228.9
XS GIS Cut Line= 4
     1760232.649      127558.275     1760170.887      127932.968
     1759952.659      128163.548     1759895.014      128525.889
#Sta/Elev= 30
      10 1742.28      60 1709.07    89.9 1684.86    99.9 1677.83   179.9 1626.63
   189.9 1622.27   229.8 1608.44   289.8 1578.18   379.7 1538.45   419.4 1527.38
     526 1501.79   538.5 1499.52     551 1500.51   578.2 1506.85   647.6  1520.8
   736.9 1543.36   756.7 1551.15   776.6 1563.41   806.3 1585.01   855.9 1618.52
   925.3 1667.92   935.2 1676.74   945.1 1687.01   984.8 1731.33  1004.6 1750.48
  1014.5 1758.76  1034.4 1772.72  1044.3 1778.19  1054.2 1782.38  1064.1 1785.13
#Mann= 3 , 0 , 0
       0     .06       0     526    .045       0     551     .06       0
Bank Sta=526,551
XS Rating Curve= 0 ,0
Exp/Cntr=0.3,0.1

Type RM Length L Ch R = 1 ,7146.7  ,335.5,338.9,342.2
XS GIS Cut Line= 3
     1759837.369      127438.867     1759849.981      127935.839
     1759862.074      128464.126
#Sta/Elev= 30
     9.9 1756.71    49.7 1728.01   109.4 1686.62   139.2  1667.9   188.9 1639.01
   248.6 1608.15   288.3 1586.19   308.2 1576.12   367.9  1550.2   397.7 1539.49
   467.3 1504.89   487.2 1493.64   494.6  1491.3   497.1 1490.51   507.1 1490.45
   519.6 1493.19   586.9 1511.18   666.6 1530.72   746.4 1545.62   756.4 1547.81
   766.3 1551.25   776.3 1556.64   786.3 1562.98     876 1622.57   945.8 1672.14
   955.8 1679.55   965.7 1687.93   995.6 1717.39  1005.6 1726.56  1025.6 1743.37
#Mann= 3 , 0 , 0
       0     .06       0   494.6    .045       0   519.6     .06       0
Bank Sta=494.6,519.6
XS Rating Curve= 0 ,0
Exp/Cntr=0.3,0.1

Type RM Length L Ch R = 1 ,6807.7  ,354.5,361,367.6
XS GIS Cut Line= 4
     1759590.318      127389.457     1759532.673      127760.033
     1759499.733      128101.786     1759462.675      128377.659
#Sta/Elev= 30
     9.9  1745.2    39.5 1713.72    69.1 1684.89    98.7 1654.85   108.6 1647.28
   118.4 1641.71     148 1628.92   246.7 1592.81   335.6 1549.91   395.2 1523.57
   435.6 1503.22   445.7 1499.55   455.8 1496.98   544.3 1481.64   556.8 1480.02
   569.3 1481.45     577  1483.8   597.2 1492.72   627.5 1504.76   667.9 1519.68
     678 1522.09   718.4 1525.53   728.3 1527.55   738.3 1531.66   758.1 1544.34
   797.9 1574.76   837.7 1604.03   867.5 1627.13   907.2 1655.62   996.7  1727.8
#Mann= 3 , 0 , 0
       0     .06       0   544.3    .045       0   569.3     .06       0
Bank Sta=544.3,569.3
XS Rating Curve= 0 ,0
Exp/Cntr=0.3,0.1

Type RM Length L Ch R = 1 ,6446.7  ,588.8,596.4,606.5
XS GIS Cut Line= 3
     1759351.503      127319.459     1759183.537      127823.768
     1759030.337      128282.956
#Sta/Elev= 30
      10 1764.19    50.1  1729.6   120.3 1671.86   140.4 1656.12   180.5  1626.2
   190.6  1619.2   200.6 1613.29   230.7    1597   250.7 1584.96   270.8 1571.87
   310.9 1544.53     341 1525.48     351 1519.92     361 1515.78   391.1 1507.77
   451.3 1493.34   521.5 1469.93   529.1 1468.29   541.6 1467.49   554.1  1469.1
     703 1492.29   723.2 1496.65   733.2 1499.91   753.4 1507.49   783.7 1520.56
   884.5 1567.73   934.9 1592.34   975.3 1609.17   995.4 1618.38  1015.6 1625.37
#Mann= 3 , 0 , 0
       0     .06       0   529.1    .045       0   554.1     .06       0
Bank Sta=529.1,554.1
XS Rating Curve= 0 ,0
Exp/Cntr=0.3,0.1

Type RM Length L Ch R = 1 ,5850.3  ,581.7,597.1,610.9
XS GIS Cut Line= 3
     1758969.703      127101.882     1758681.839      127523.401
     1758365.581      127908.763
#Sta/Elev= 30
      10 1716.68      30 1701.13    70.1 1671.67   120.1 1637.11   170.1 1606.05
   220.2  1577.2   250.2 1561.64   330.3 1523.43   370.3 1501.56   470.4 1459.27
   497.9 1446.98   510.4 1443.68   520.4 1444.48   522.9 1445.43   530.4  1448.3
   550.3 1457.66   570.3 1465.05   590.2  1471.5   640.1  1485.6   699.9 1504.89
   719.8 1513.33   759.7 1532.14   829.5 1559.97   869.4 1578.49   889.3 1589.68
   899.3 1596.21   909.3 1603.66   929.2 1621.44     989 1678.41    1009 1694.99
#Mann= 3 , 0 , 0
       0     .06       0   497.9    .045       0   522.9     .06       0
Bank Sta=497.9,522.9
XS Rating Curve= 0 ,0
Exp/Cntr=0.3,0.1

Type RM Length L Ch R = 1 ,5253.2  ,595.4,591.4,588.4
XS GIS Cut Line= 3
     1758733.877      126961.236     1758232.157      127185.334
      1757770.38      127377.105
#Sta/Elev= 30
      10 1678.17    79.9 1622.11    99.9 1608.05   129.9 1592.31   169.8 1576.59
   189.8 1566.94   239.8 1535.05   249.8 1529.84   389.6 1469.71   449.6  1445.4
   489.5 1432.15     537 1423.23   549.5 1422.88     562 1424.93   589.5 1431.55
   619.5 1434.94   629.5 1439.02   719.5 1490.99   749.5 1504.79   789.5 1525.12
   809.5 1533.25   839.5 1540.88   899.5 1547.38   909.5 1549.29   919.5 1552.56
   939.5 1562.49   969.5 1580.81   999.5 1596.93  1019.5 1606.25  1049.5 1617.54
#Mann= 3 , 0 , 0
       0     .06       0     537    .045       0     562     .06       0
Bank Sta=537,562
XS Rating Curve= 0 ,0
Exp/Cntr=0.3,0.1

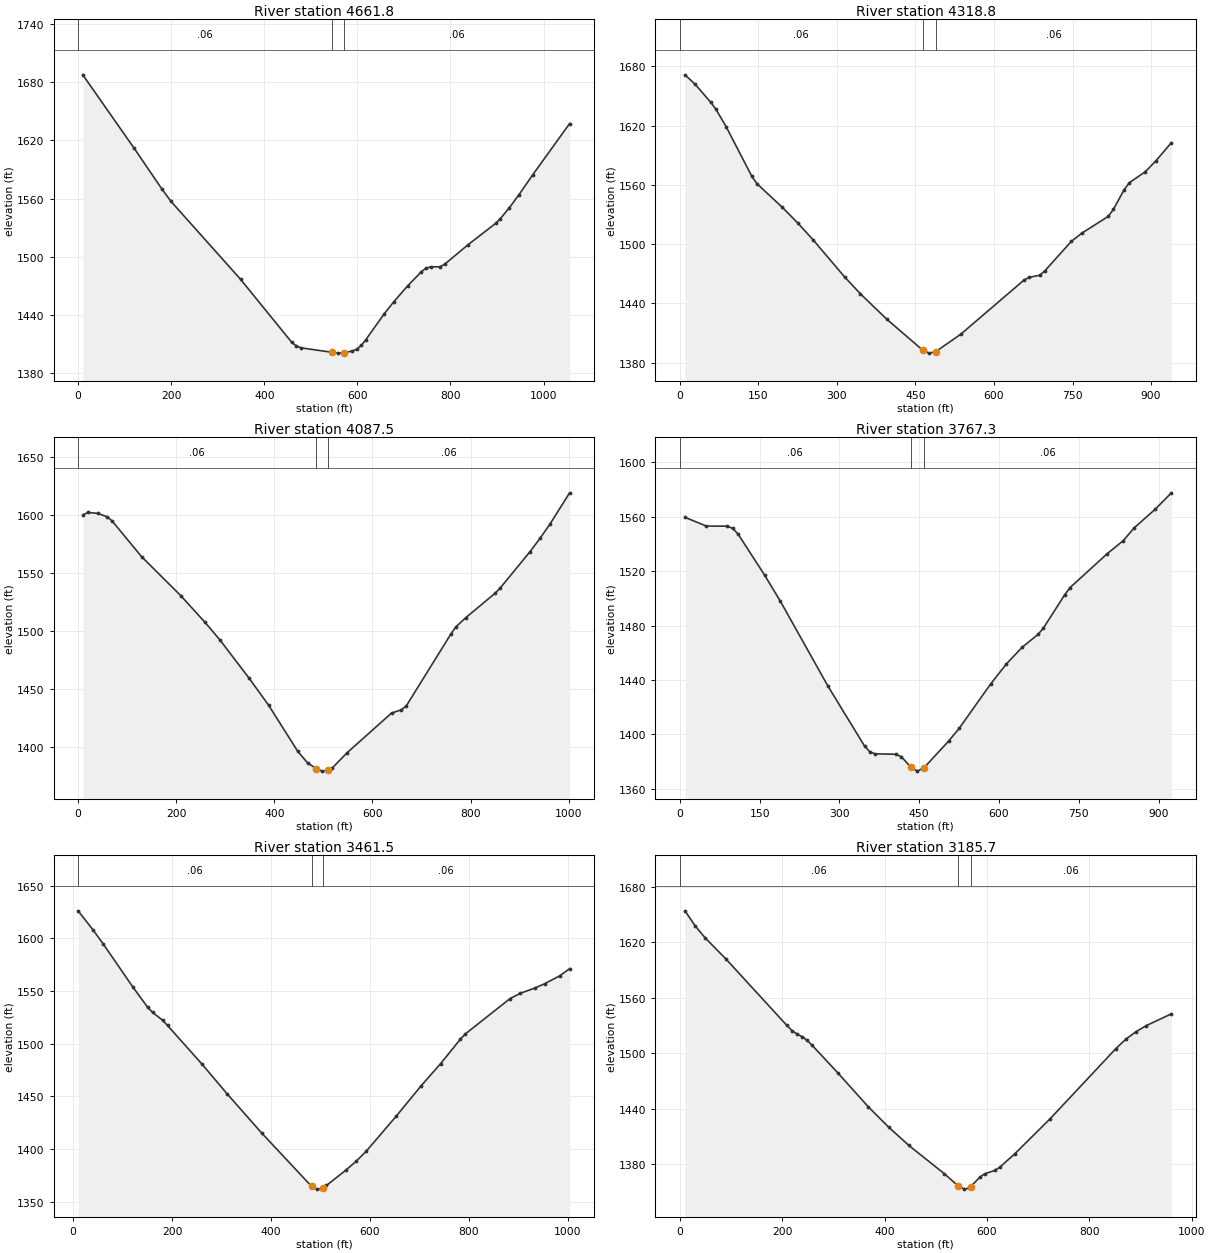
Type RM Length L Ch R = 1 ,4661.8  ,352.3,343.1,331.8
XS GIS Cut Line= 3
     1758285.069      126561.838     1757817.434       126867.27
     1757382.734      127109.202
#Sta/Elev= 30
      10 1687.66   119.7 1612.36   179.5 1570.17   199.5 1557.08   349.1 1476.61
   458.8 1411.73   468.8 1407.91   478.8 1405.98     546 1401.33   558.5  1400.5
     571 1401.04   588.4 1402.57   598.3  1404.4   608.3 1408.41   618.2 1414.44
     658 1441.26   677.9  1453.3   707.8 1469.82   737.6 1484.58   747.6  1488.2
   757.5 1489.55   777.4 1489.64   787.4 1492.17   837.1 1512.12   896.8 1534.29
   906.8 1539.05   926.7 1550.69   946.6 1563.61   976.4 1584.32    1056 1637.43
#Mann= 3 , 0 , 0
       0     .06       0     546    .045       0     571     .06       0
Bank Sta=546,571
XS Rating Curve= 0 ,0
Exp/Cntr=0.3,0.1

Type RM Length L Ch R = 1 ,4318.8  ,234.4,231.2,227.3
XS GIS Cut Line= 4
     1757873.318      126240.673     1757712.735      126463.018
     1757515.095      126718.304     1757313.337      126994.176
#Sta/Elev= 30
     9.8 1671.31    29.4 1661.61    58.8 1643.63    68.6 1636.72    88.2 1619.02
   137.1 1569.02   146.9 1561.34   195.9 1537.15   225.3 1521.35   254.7 1504.26
   314.6  1466.9   344.9 1449.76   395.3 1424.02   463.6 1392.88   476.1 1389.73
   488.6 1391.18   536.6 1408.87   657.4 1463.66   667.5 1466.41   687.6 1468.56
   697.6 1473.24   747.9 1502.87     768 1511.18   818.3 1528.05   828.3 1535.33
   848.4 1554.89   858.5 1562.13   888.6 1573.09   908.7 1583.91   938.9  1602.7
#Mann= 3 , 0 , 0
       0     .06       0   463.6    .045       0   488.6     .06       0
Bank Sta=463.6,488.6
XS Rating Curve= 0 ,0
Exp/Cntr=0.3,0.1

Type RM Length L Ch R = 1 ,4087.5  ,331.5,320.3,309.8
XS GIS Cut Line= 3
      1757655.09      126067.738     1757397.585      126493.654
     1757149.299      126932.639
#Sta/Elev= 30
      10 1599.91    19.9    1602    39.8 1601.24    59.7 1598.23    69.7 1594.53
   129.4 1563.97     209 1530.52   258.8 1507.42   288.7  1492.5   348.4 1459.46
   388.2 1436.19   447.9  1396.3   467.8 1386.46   485.2 1381.57   497.7 1379.37
   510.2 1380.04   517.9 1382.02   548.1 1395.09   638.9 1429.36   659.1 1432.16
   669.2 1435.68     760 1497.46     770 1503.52   790.2 1511.45   850.7 1532.72
   860.8 1537.21   921.4 1568.38   941.5 1579.68   961.7 1591.91    1002 1618.92
#Mann= 3 , 0 , 0
       0     .06       0   485.2    .045       0   510.2     .06       0
Bank Sta=485.2,510.2
XS Rating Curve= 0 ,0
Exp/Cntr=0.3,0.1

Type RM Length L Ch R = 1 ,3767.3  ,315.4,305.8,295.8
XS GIS Cut Line= 4
     1757185.694      125952.447     1757123.932      126203.615
     1757070.404      126594.778     1757029.229      126862.416
#Sta/Elev= 30
     9.9 1559.55    49.7 1553.18    89.5 1553.09    99.5  1551.4   109.4 1547.31
   159.2 1517.19     189 1497.83   278.4 1435.43   347.5 1391.15   357.4    1387
   367.2 1385.58   406.7 1385.26   416.6 1383.37   433.7 1376.06   446.2 1372.85
   458.7 1375.16   505.4 1394.99   525.1 1404.26   584.4 1437.01     614 1451.75
   643.6 1463.98   673.5 1473.47   683.5 1478.06   723.7 1502.67   733.7 1507.93
   803.9 1532.96     834 1542.53     854 1551.78   894.2  1565.7   924.2 1577.63
#Mann= 3 , 0 , 0
       0     .06       0   433.7    .045       0   458.7     .06       0
Bank Sta=433.7,458.7
XS Rating Curve= 0 ,0
Exp/Cntr=0.3,0.1

Type RM Length L Ch R = 1 ,3461.5  ,277.6,275.8,274.4
XS GIS Cut Line= 3
     1756691.594       125898.92     1756795.456      126379.936
     1756909.595       126878.87
#Sta/Elev= 30
      10  1626.1    40.2 1607.97    60.3 1594.99   120.5  1553.9   150.6 1534.57
   160.7 1529.64   180.8 1522.27   190.8 1517.29   261.1 1480.27   311.3 1452.39
   381.6 1414.99   482.1 1364.57   492.1 1361.94   502.1 1362.47   504.6  1363.2
   512.2 1365.41   552.3 1380.32   572.4 1388.47   592.5 1397.89   652.7 1430.88
   702.9 1459.65     743 1481.09   783.1 1504.32   793.2 1509.34   883.5 1542.83
   903.6 1547.71   933.7 1552.83   953.7 1556.98   983.9 1564.44  1003.9  1571.2
#Mann= 3 , 0 , 0
      10     .06       0   482.1    .045       0   504.6     .06       0
Bank Sta=482.1,504.6
XS Rating Curve= 0 ,0
Exp/Cntr=0.3,0.1

Type RM Length L Ch R = 1 ,3185.7  ,480.4,498.2,516.1
XS GIS Cut Line= 3
     1756510.423      125894.802     1756489.836      126302.435
     1756584.538      126644.188
#Sta/Elev= 30
      10 1654.09    29.9 1637.81    49.8 1624.57    89.6 1602.21   209.1 1529.99
     219 1524.47     229 1520.57   238.9 1517.84   248.9 1513.73   258.8 1508.27
   308.6 1478.68   368.3 1441.79   408.2 1419.74   447.6 1399.99   516.5 1369.55
   543.4 1356.41   555.9 1352.74   565.8 1354.08   568.4 1355.46   585.5 1365.37
   595.3 1369.28     615 1372.94   624.9 1376.35   654.4 1390.98   723.4  1428.9
   851.7 1504.79   871.5 1515.21   891.3 1523.16     911  1529.7   960.4 1542.56
#Mann= 3 , 0 , 0
       0     .06       0   543.4    .045       0   568.4     .06       0
Bank Sta=543.4,568.4
XS Rating Curve= 0 ,0
Exp/Cntr=0.3,0.1