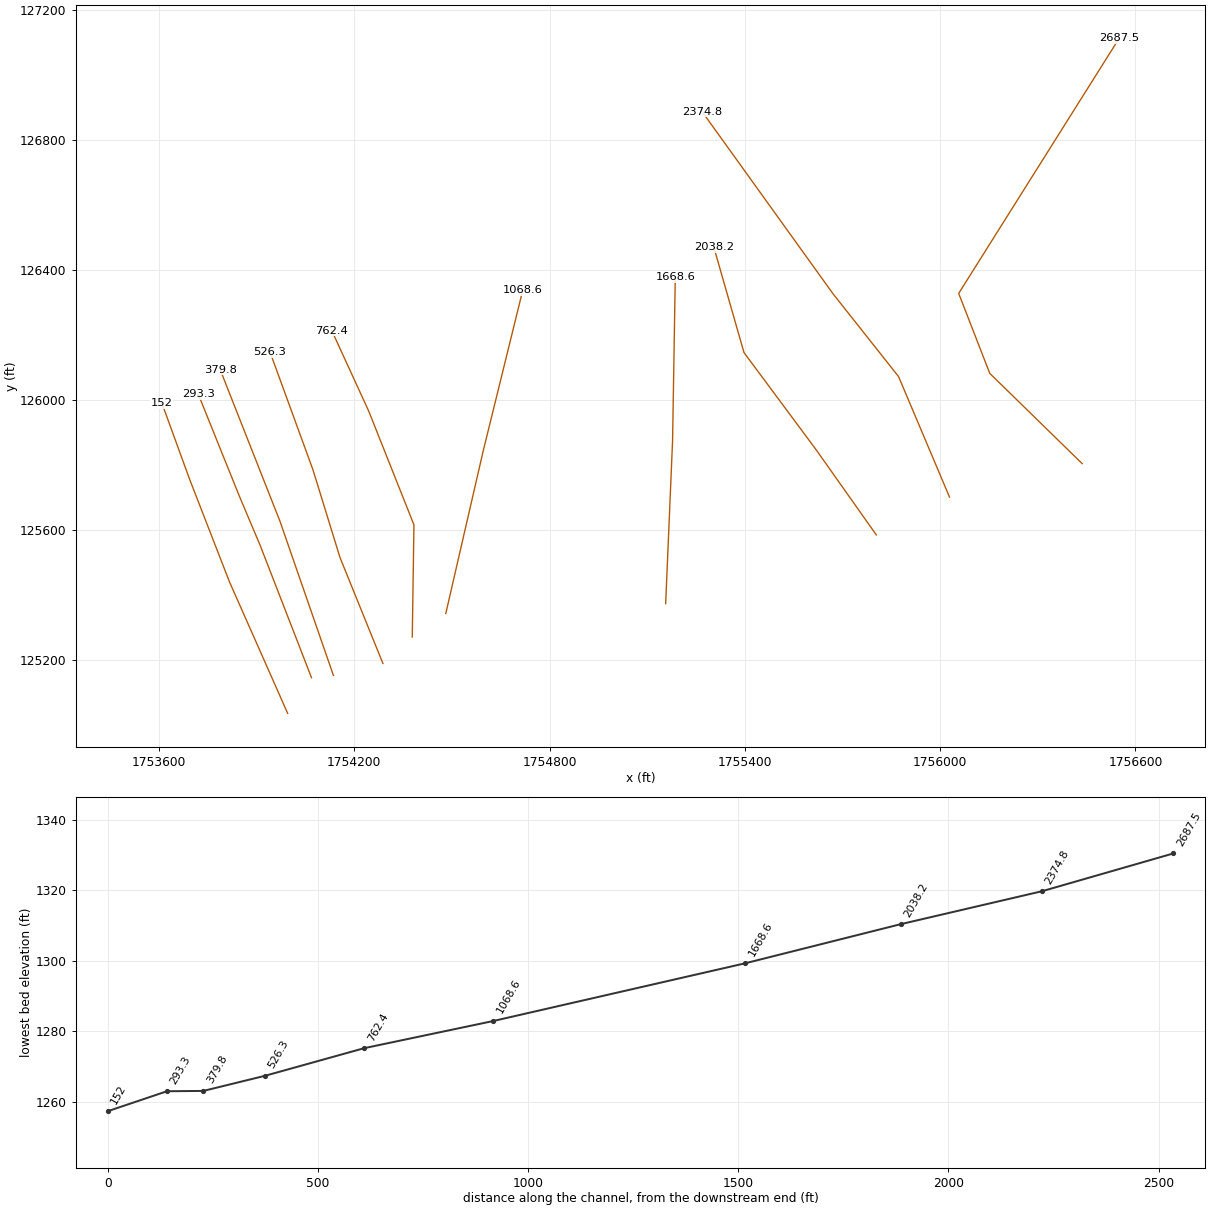
HEC-RAS study Bartley Creek.prj: Bartley Creek

--- Bartley Creek.g01 (geometry) --- (continued)

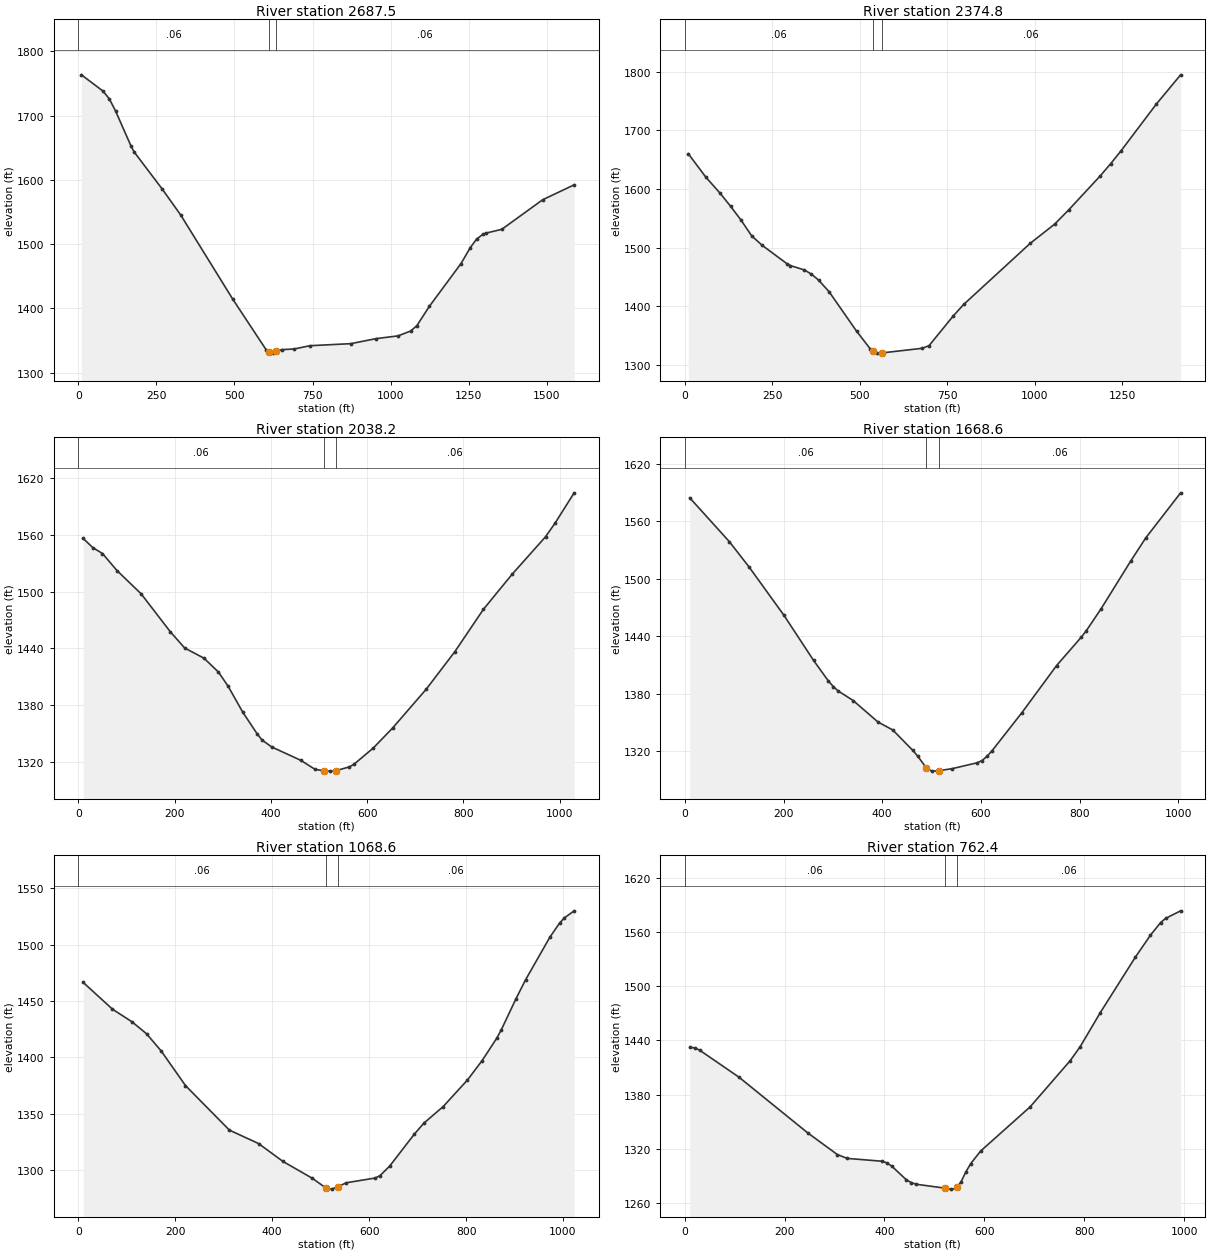
Type RM Length L Ch R = 1 ,2687.5  ,304.4,312.7,321
XS GIS Cut Line= 4
     1756436.308      125804.217     1756152.388       126081.83
     1756056.872      126327.855     1756549.857      127112.502
#Sta/Elev= 30
     9.9 1763.41    79.4 1737.97    99.3 1725.94   119.1  1707.3   168.8 1652.52
   178.7 1643.46     268 1586.14   327.6 1545.52   494.8 1414.22   602.4    1335
   609.4 1332.04   621.9 1330.51   634.4 1333.23   651.2 1335.91   691.2 1336.95
   741.6 1342.04   872.5 1345.25   953.1 1353.03  1023.6 1357.33  1063.9 1364.85
    1084 1373.23  1124.3 1403.47  1225.1 1469.67  1255.3 1494.75  1275.4 1507.93
  1295.6 1515.31  1305.6 1517.22    1356 1523.09  1486.9 1569.09  1587.7 1592.32
#Mann= 3 , 0 , 0
       0     .06       0   609.4    .045       0   634.4     .06       0
Bank Sta=609.4,634.4
XS Rating Curve= 0 ,0
Exp/Cntr=0.3,0.1

Type RM Length L Ch R = 1 ,2374.8  ,337.6,336.6,335.6
XS GIS Cut Line= 4
     1756028.675      125701.279      1755872.21      126071.855
     1755670.452       126327.14     1755268.481      126887.121
#Sta/Elev= 30
    10.1 1659.97    60.3 1619.98   100.6 1592.88   130.7 1570.48   160.9 1546.61
   191.1 1519.93   221.2 1503.72   291.6 1472.55   301.7 1469.22   341.9 1461.66
     362 1454.53   382.1 1444.52   412.1  1424.8     491  1357.2   530.4  1326.7
   537.7 1322.61   550.2 1319.77   562.7 1320.07   678.3    1328   698.1 1332.53
   767.6 1383.55   797.6 1403.18   987.4 1507.24  1057.3 1540.05  1097.3 1564.34
  1187.2  1622.2  1217.2 1643.15  1247.1 1665.34    1347 1744.36    1417 1794.72
#Mann= 3 , 0 , 0
       0     .06       0   537.7    .045       0   562.7     .06       0
Bank Sta=537.7,562.7
XS Rating Curve= 0 ,0
Exp/Cntr=0.3,0.1

Type RM Length L Ch R = 1 ,2038.2  ,388.4,369.7,351.7
XS GIS Cut Line= 4
     1755803.756       125584.96     1755618.469      125847.451
     1755397.153       126145.97     1755304.509      126470.224
#Sta/Elev= 30
      10 1556.11    30.1  1546.4    50.2 1540.16    80.3 1522.18   130.5  1497.6
   190.8 1457.76   220.9 1440.41   261.1 1429.63   291.2 1414.95   311.3 1399.95
   341.4  1372.8   371.5 1349.76   381.6 1343.26   401.6 1335.95   461.9 1321.88
     492 1312.21   509.7 1310.86   522.2  1310.4   534.7 1310.78   562.3 1314.79
   572.4 1317.51   612.6 1334.72   652.7 1355.79   722.7 1396.87   782.2 1436.53
   841.7 1481.33   901.2 1518.26   970.6 1557.85   990.5  1572.3  1030.1 1604.25
#Mann= 3 , 0 , 0
       0     .06       0   509.7    .045       0   534.7     .06       0
Bank Sta=509.7,534.7
XS Rating Curve= 0 ,0
Exp/Cntr=0.3,0.1

Type RM Length L Ch R = 1 ,1668.6  ,604.7,600,594.1
XS GIS Cut Line= 3
     1755156.598      125373.371     1755177.818      125874.699
      1755186.13       126377.58
#Sta/Elev= 30
      10 1584.52    90.3 1538.75   130.5 1512.16   200.7 1462.08   260.9 1414.89
     291 1393.34   301.1 1387.43   311.1 1382.83   341.2 1372.98   391.4 1350.58
   421.5 1342.23   461.6 1321.15   471.7 1315.08   489.3 1302.81   491.7 1301.29
   501.8  1299.3   514.3 1299.74     542  1301.9   592.3 1307.99   602.4 1310.39
   612.4 1314.75   622.5  1320.5   682.8 1360.12   753.3 1409.43   803.5 1439.17
   813.6 1445.85   843.8 1468.93   904.1 1518.99   934.3 1542.87  1004.7 1589.72
#Mann= 3 , 0 , 0
       0     .06       0   489.3    .045       0   514.3     .06       0
Bank Sta=489.3,514.3
XS Rating Curve= 0 ,0
Exp/Cntr=0.3,0.1

Type RM Length L Ch R = 1 ,1068.6  ,289.5,306.1,323.2
XS GIS Cut Line= 3
     1754481.008      125343.056     1754595.864      125842.661
     1754717.693      126338.318
#Sta/Elev= 30
    10.1 1466.48    70.4 1442.72   110.6 1431.54   140.7 1420.91   170.9 1405.63
   221.1 1374.86   311.6 1335.32   371.9 1323.36   422.2 1307.48   482.5  1292.6
   510.1 1284.12   522.6 1282.89   535.1 1284.97   552.7 1288.53   612.7 1292.76
   622.7 1294.97   642.7 1303.51   692.8  1331.5   712.8 1341.45   752.8 1356.24
   802.9 1379.85   832.9 1396.93   862.9 1416.68   872.9  1424.6     903 1452.04
     923    1469     973 1506.74     993 1519.25    1003 1523.86    1023 1530.08
#Mann= 3 , 0 , 0
       0     .06       0   510.1    .045       0   535.1     .06       0
Bank Sta=510.1,535.1
XS Rating Curve= 0 ,0
Exp/Cntr=0.3,0.1

Type RM Length L Ch R = 1 ,762.4   ,238.3,236.2,234
XS GIS Cut Line= 4
      1754378.07         125271.     1754383.217      125615.841
     1754244.251      125965.829     1754131.019       126212.88
#Sta/Elev= 30
     9.9 1432.25    19.7 1431.89    29.6 1429.32   108.4 1399.39   246.3 1337.54
   305.5 1313.57   325.2 1309.28   394.4 1306.17   404.3  1304.4   414.2 1300.87
     444 1285.45   453.9 1282.38   463.8  1280.6   520.7 1276.31   533.2  1275.2
   543.1 1275.94   545.7 1277.76     553 1282.89   562.9 1294.16   572.8 1303.55
   592.6 1317.44   691.7 1366.39   771.8  1417.5   791.9 1433.05   832.2 1470.83
   902.6 1532.49   932.8 1556.77   952.9 1570.65     963 1575.35   993.2 1583.78
#Mann= 3 , 0 , 0
       0     .06       0   520.7    .045       0   545.7     .06       0
Bank Sta=520.7,545.7
XS Rating Curve= 0 ,0
Exp/Cntr=0.3,0.1

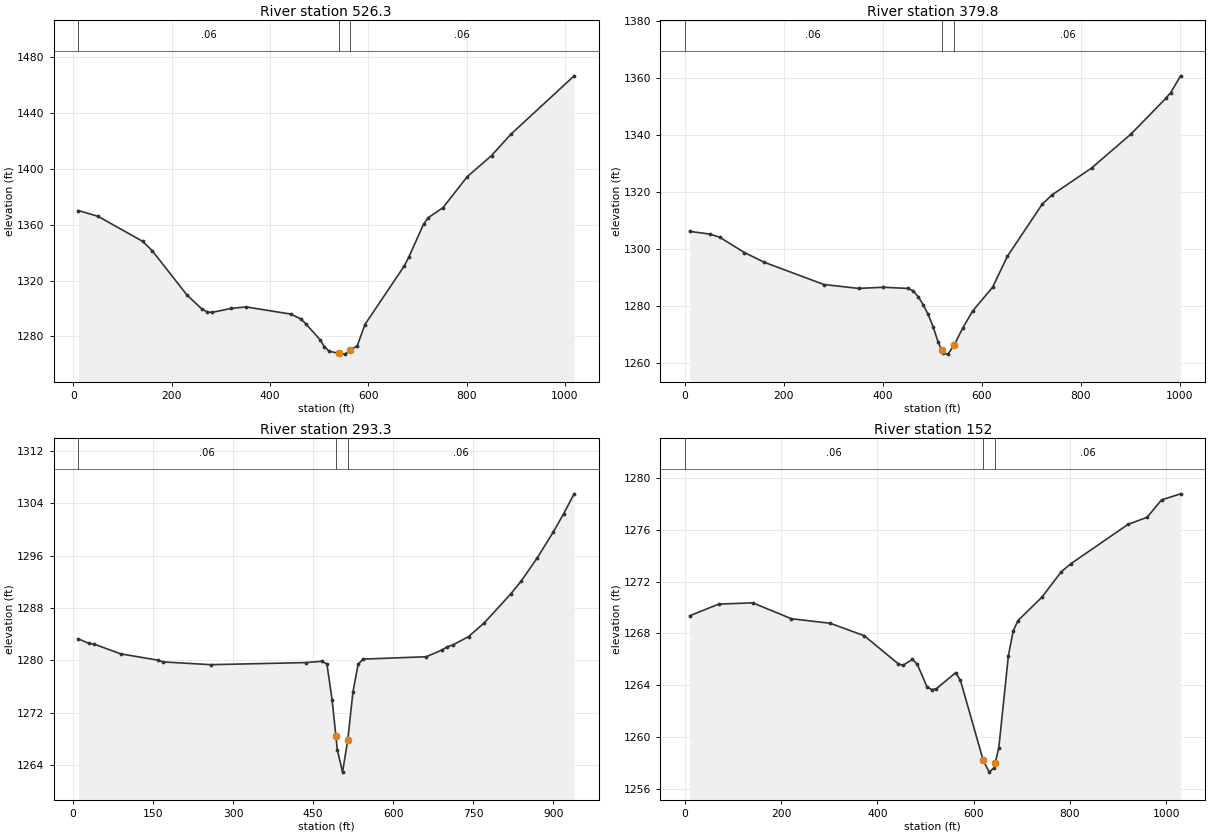
Type RM Length L Ch R = 1 ,526.3   ,144.4,146.5,148.6
XS GIS Cut Line= 4
      1754287.89      125189.571     1754155.898      125515.667
      1754073.08      125784.826     1753941.089      126147.155
#Sta/Elev= 30
    10.1 1370.25    50.3 1366.07   140.7 1348.22   160.8 1341.33   231.2  1309.7
   261.3 1299.75   271.4 1297.73   281.4  1297.2   321.6 1300.16   351.8 1301.16
   442.3 1296.04   462.4 1292.62   472.5 1289.28   502.7 1277.43  510.58 1272.69
   520.5  1269.4   540.4 1267.93   552.9 1267.35     563 1270.11  577.63 1273.26
   593.2 1288.55     673 1330.37   682.8 1337.03   712.5 1360.41   722.4 1365.21
   752.1 1372.29   801.5 1394.52   850.9 1409.61   890.5 1425.01    1019 1466.76
#Mann= 3 , 0 , 0
    10.1     .06       0   540.4    .045       0     563     .06       0
Bank Sta=540.4,563
XS Rating Curve= 0 ,0
Exp/Cntr=0.3,0.1

Type RM Length L Ch R = 1 ,379.8   ,85.9,86.5,87.2
XS GIS Cut Line= 3
     1754135.764      125152.849      1753971.54      125627.118
     1753788.184      126092.558
#Sta/Elev= 30
      10 1306.18    50.2 1305.24    70.3 1304.15   120.5 1298.75   160.6 1295.34
   281.1 1287.52   351.3 1286.15   401.5 1286.55   451.7 1286.13   461.7 1285.28
   471.8 1283.23   481.8 1280.44   491.9 1277.02   501.9  1272.7   511.9 1267.36
   519.4 1264.46   521.9 1263.49   531.9 1263.06   544.4 1266.21   561.9 1272.27
   581.9 1278.24     622 1286.51     652 1297.41     722 1315.63     742 1318.97
   822.1 1328.42   902.1 1340.41   972.1 1352.89   982.1 1354.93  1002.2 1360.83
#Mann= 3 , 0 , 0
       0     .06       0   519.4    .045       0   544.4     .06       0
Bank Sta=519.4,544.4
XS Rating Curve= 0 ,0
Exp/Cntr=0.3,0.1

Type RM Length L Ch R = 1 ,293.3   ,137.6,141.2,144.9
XS GIS Cut Line= 4
      1754068.52       125145.61     1753910.716      125552.846
     1753846.237      125705.559     1753720.673      126017.774
#Sta/Elev= 30
     9.9  1283.3    29.8  1282.6    39.7 1282.49    89.3 1281.01   158.8 1280.05
   168.7 1279.78   258.1 1279.36   436.7 1279.68     466 1279.88   475.7 1279.47
   485.5 1273.98   492.5  1268.5   495.2 1266.38  504.99 1262.97   514.8 1267.89
   524.5 1275.22   534.3 1279.46     544 1280.21   661.9 1280.57   691.6 1281.61
   701.5  1282.1   711.4 1282.36   741.1 1283.64   770.8 1285.76   820.3 1290.16
   840.1 1292.15   869.7 1295.64   899.4 1299.53   919.2 1302.37     939 1305.42
#Mann= 3 , 0 , 0
     9.9     .06       0   492.5    .045       0   514.8     .06       0
Bank Sta=492.5,514.8
XS Rating Curve= 0 ,0
Exp/Cntr=0.3,0.1

Type RM Length L Ch R = 1 ,152     ,171.7,152,132.4
XS GIS Cut Line= 4
     1753995.232      125035.968     1753816.216      125441.109
     1753693.732      125756.742     1753608.935      125989.933
#Sta/Elev= 30
    10.1 1269.37    70.5 1270.27   140.9 1270.37   221.5 1269.14     302 1268.79
   372.5 1267.83   442.9 1265.67   452.9 1265.54   472.8    1266   482.8 1265.62
   502.7  1263.9   512.6 1263.66   522.6 1263.74   562.4 1264.97   572.4 1264.38
   619.6 1258.21   632.1 1257.29   642.1 1257.62   644.6 1258.01     652 1259.15
     672  1266.3   681.9 1268.19   691.9    1269   741.7 1270.81   781.5 1272.76
   801.3 1273.38   920.4 1276.43   960.1 1276.98   989.9 1278.32  1029.6 1278.79
#Mann= 3 , 0 , 0
       0     .06       0   619.6    .045       0   644.6     .06       0
Bank Sta=619.6,644.6
XS Rating Curve= 0 ,0
Exp/Cntr=0.3,0.1

Chan Stop Cuts=-1
Use User Specified Reach Order=0